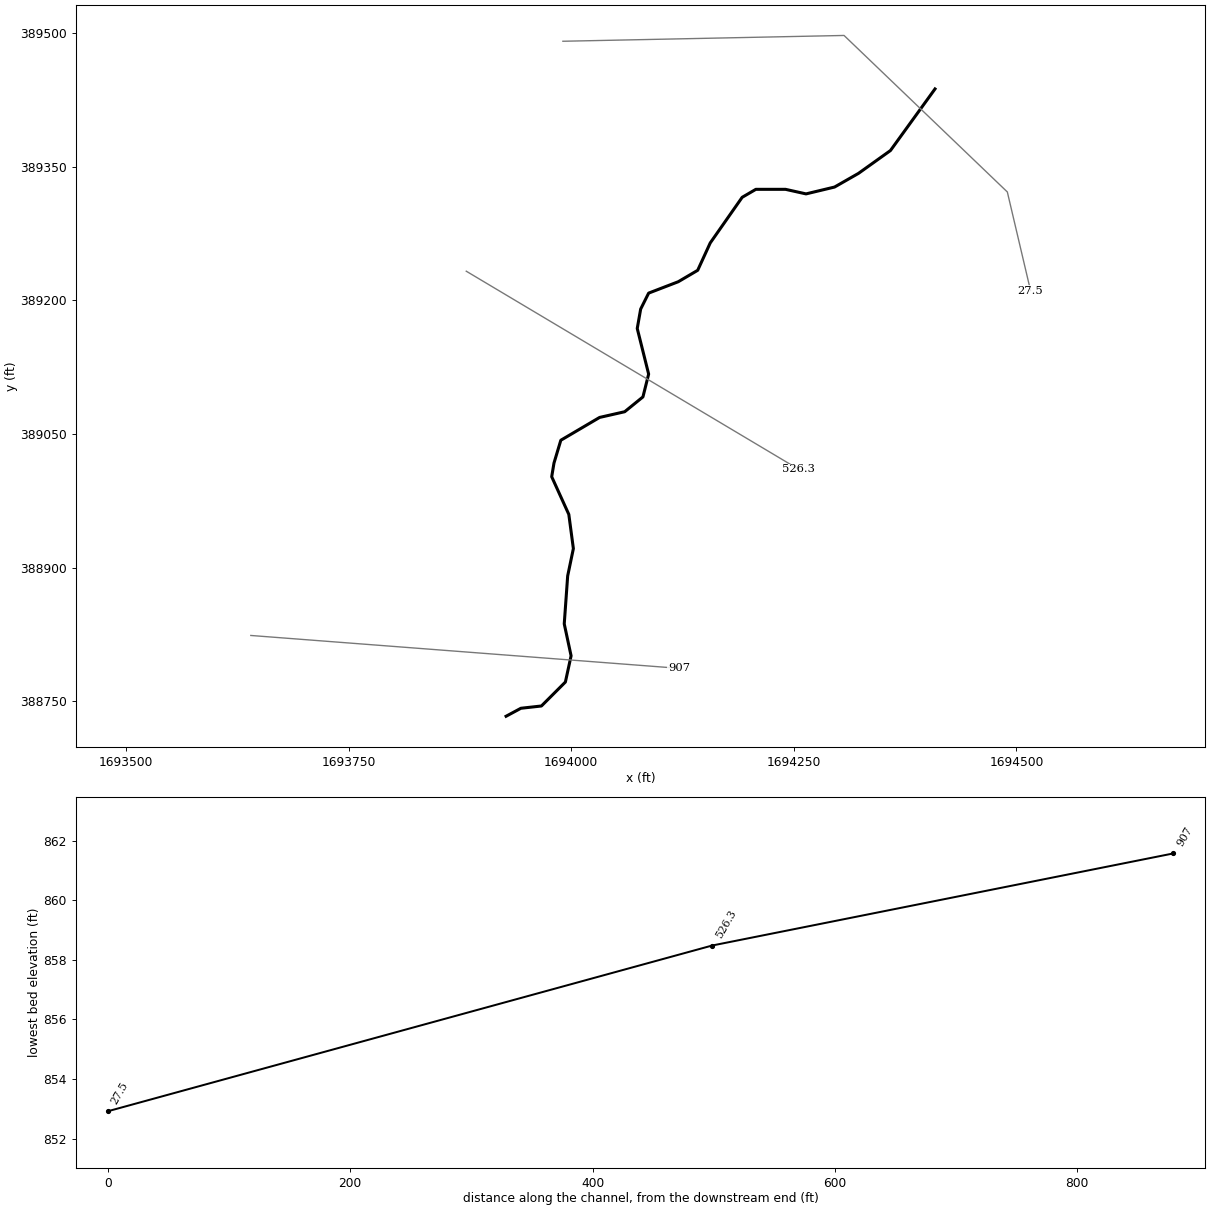
--- LUKEYFK.prj (project) ---

Proj Title=LUKEYFK
Current Plan=p01
Default Exp/Contr=0,0
English Units
Geom File=g01
Flow File=f01
Plan File=p01
BEGIN DESCRIPTION:
END DESCRIPTION:
DSS Export Rating Curves= 0
DSS Export Rating Curve Sorted= 0
DSS Export Volume Flow Curves= 0
DXF OffsetX= 0
DXF OffsetY= 0
DXF ScaleX= 0
DXF ScaleY= 0

--- LUKEYFK.p01 (plan) ---

Plan Title=Floodplain
Program Version=4.00
Geom File=g01
Flow File=f01
K Sum by GR=0
Std Step Tol=0.01
Critical Tol=0.01
Num of Std Step Trials=20
Max Error Tol=0.3
Flow Tol Ratio=0.001
Split Flow NTrial=30
Split Flow Tol=0.02
Split Flow Ratio=0.02
Log Output Level=0
Friction Slope Method=1
Unsteady Friction Slope Method=2
Unsteady Bridges Friction Slope Method=1
Global Log Level=0
CheckData=False
Run HTab=0
Run UNet=0
Run PostProcess=0
UNET Theta=0
UNET Theta Warmup=0
UNET ZTol=0
UNET ZSATol=0
UNET MxIter=0
UNET MaxInSteps=0
UNET DtIC=0
UNET DtMin=0
UNET MaxCRTS=0
UNET WFStab=0
UNET SFStab=0
UNET WFX=0
UNET SFX=0
UNET DSS MLevel=0
UNET DZMax Abort=0
UNET Convert EG Bridges=0
UNET Use Existing IB Tables=0
UNET Froude Limit=0
UNET Froude Power=0
Write IC File=0
Echo Input=False
Echo Output=False
Write Detailed=0

--- LUKEYFK.f01 (steady flow) ---

Flow Title=NFF Regression Equation
Program Version=4.10
Number of Profiles= 1
Profile Names=P100yr
River Rch & RM=LUKEYFK,Main            ,907
899.6475
Boundary for River Rch & Prof#=LUKEYFK,Main            , 1
Up Type= 0
Dn Type= 3
Dn Slope=0.00108
DSS Import GetInterval= 0
DSS Import GetPeak= 0
DSS Import FillOption= 0

--- LUKEYFK.g01 (geometry) ---

Geom Title=USGS 10m DEM
Program Version=4.10

River Reach=LUKEYFK         ,Main
Reach XY= 30
     1693926.787      388732.988     1693943.438      388741.955
     1693966.494      388744.516     1693993.392      388771.414
     1693999.796      388800.874     1693992.111      388836.737
     1693995.953      388890.533     1694002.358      388921.274
     1693997.234      388959.699     1693978.021      389001.967
     1693980.583      389017.338     1693988.268      389042.955
     1694031.817      389068.572     1694059.996      389074.976
     1694080.489      389091.627     1694086.894      389117.244
     1694074.085      389168.478     1694077.928      389190.253
     1694086.894      389208.185     1694120.196      389220.993
     1694141.971      389233.802      1694156.06      389264.542
     1694191.924      389315.776     1694207.294      389324.742
     1694240.596      389324.742     1694263.651      389319.618
     1694295.673      389327.304     1694322.571      389342.674
     1694358.434      389368.291     1694408.482      389437.484

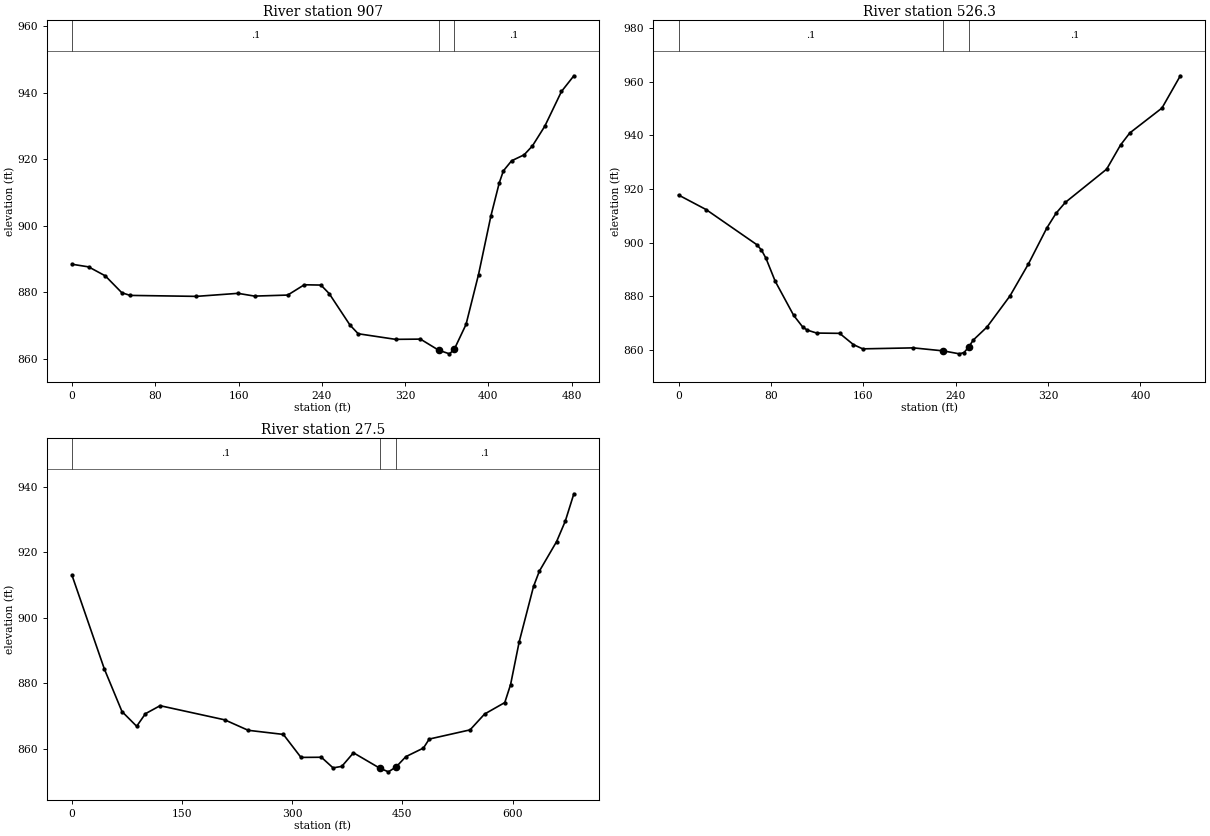
Type RM Length L Ch R = 1 ,907     ,394.2,380.7,369.3
XS GIS Cut Line= 2
     1693640.108      388823.715     1694120.794      388786.822
#Sta/Elev= 30
       0  888.46    15.9  887.67    31.9  884.98    47.8  879.91    55.8  879.11
   119.5  878.82   159.4  879.73   175.3   878.9   207.2  879.21   223.1   882.3
   239.1  882.21     247  879.67     267  870.21   274.9   867.6   310.8  865.92
   334.7  865.99   352.2  862.66   362.6  861.57   367.2  862.93   378.5  870.39
   390.5  885.37   402.4  902.96   410.4  912.86   414.4   916.5   422.3  919.52
   434.3   921.3   442.3  923.98   454.2  929.91   470.2  940.32   482.1  945.03
#Mann= 3 , 0 , 0
       0      .1       0   352.2    .045       0   367.2      .1       0
Bank Sta=352.2,367.2
XS Rating Curve= 0 ,0
Exp/Cntr=0.3,0.1

Type RM Length L Ch R = 1 ,526.3   ,501.6,498.8,493.2
XS GIS Cut Line= 2
     1693882.079      389232.786     1694255.343      389010.347
#Sta/Elev= 30
       0  917.77    23.9  912.33    67.8  899.23    71.8  897.23    75.7  894.16
    83.7  885.59    99.7  872.84   107.6  868.45   111.6  867.32   119.6  866.24
   139.5  866.13   151.5   861.9   159.5  860.34   203.3  860.71   229.3  859.58
   243.2  858.48   247.2  858.97   251.1  860.92   255.1  863.58   267.1  868.49
     287   880.1     303  892.07   318.9  905.46   326.9  910.96   334.9     915
   370.7  927.42   382.7  936.42   390.7  940.92   418.6  950.23   434.5  962.28
#Mann= 3 , 0 , 0
       0      .1       0   229.3    .045       0   251.1      .1       0
Bank Sta=229.3,251.1
XS Rating Curve= 0 ,0
Exp/Cntr=0.3,0.1

Type RM Length L Ch R = 1 ,27.5    ,24.5,27.5,30.7
XS GIS Cut Line= 4
     1693990.586      389491.032     1694306.341      389497.543
     1694489.718      389321.762     1694515.759      389211.084
#Sta/Elev= 30
       0  912.95      44  884.35      68  871.35      88  866.85    99.9  870.69
   119.9  873.14   207.9  868.82   239.9  865.62   287.8  864.36   311.8  857.33
   339.6  857.38   355.5  854.13   367.4  854.59   383.3  858.74     419  854.05
   430.9  852.92   441.5  854.45   454.7  857.57   478.6  860.19   486.5  862.94
   542.1  865.75   561.9  870.59   589.4   874.1   597.3  879.59     609  892.64
   628.6  909.62   636.5  914.27     660  923.32   671.8  929.55   683.5  937.93
#Mann= 3 , 0 , 0
       0      .1       0     419    .045       0   441.5      .1       0
Bank Sta=419,441.5
XS Rating Curve= 0 ,0
Exp/Cntr=0.3,0.1

Chan Stop Cuts=-1
Use User Specified Reach Order=0
Composite Channel Slope=5